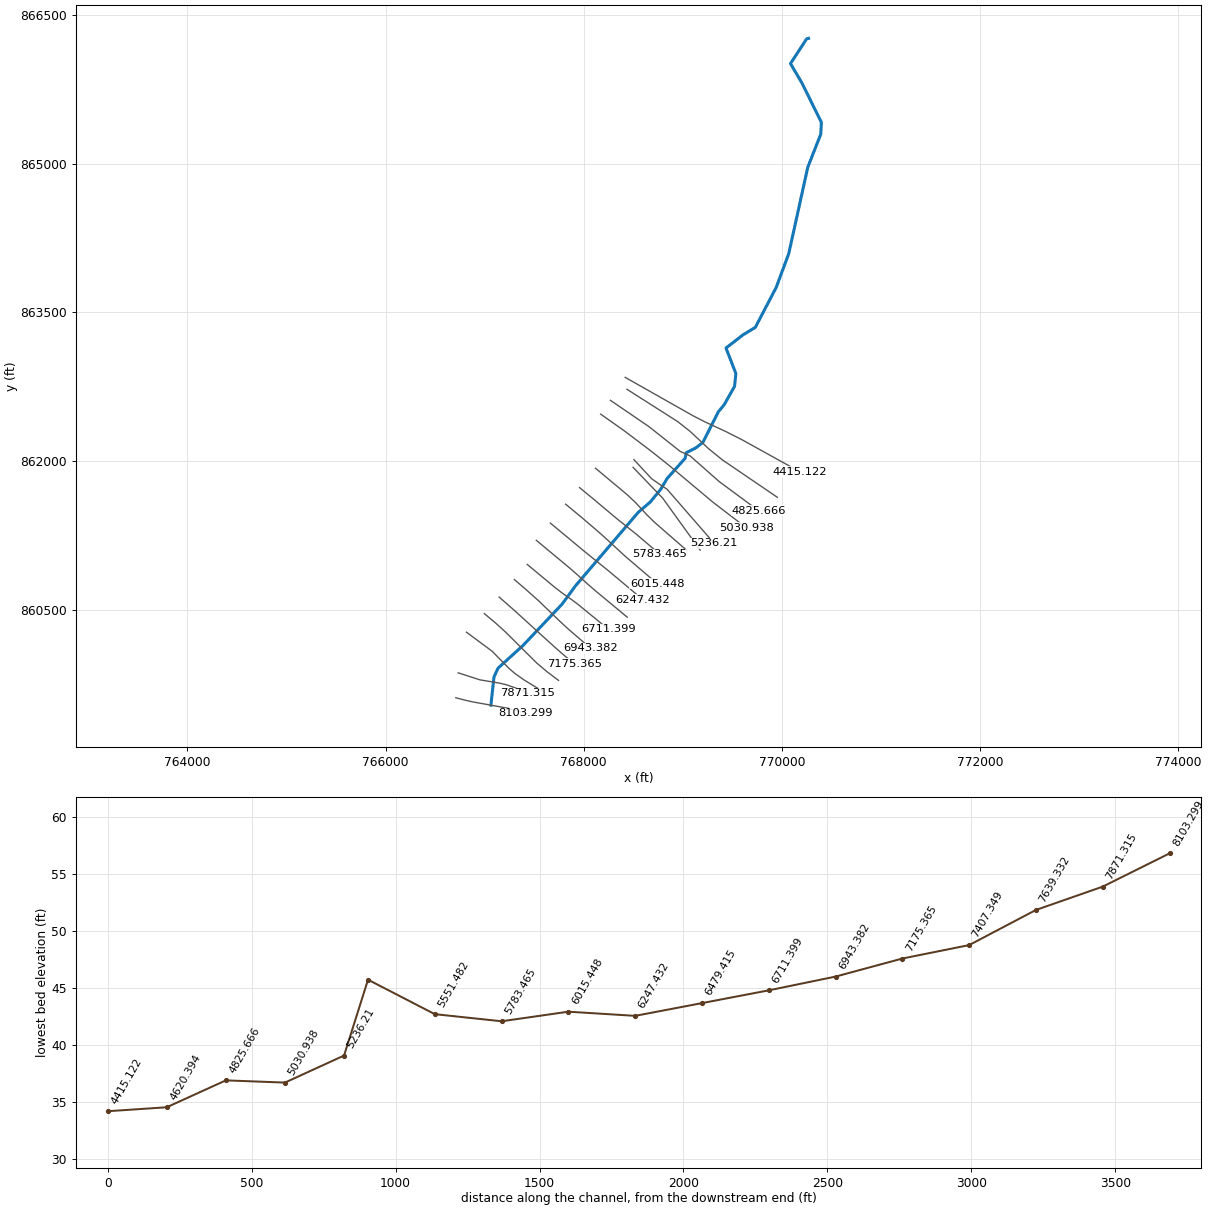
--- 16051_ras.prj (project) ---

Proj Title=16051
Current Plan=p01
Default Exp/Contr=0.3,0.1
English Units
Geom File=g01
Flow File=f01
Plan File=p01
Y Axis Title=Elevation
X Axis Title(PF)=Main Channel Distance
X Axis Title(XS)=Station
BEGIN DESCRIPTION:
RFD model 16051 exported to HEC-RAS
END DESCRIPTION:

--- 16051_ras.p01 (plan) ---

Plan Title=Plan 01
Program Version=4.10
Short Identifier=Plan 01
Geom File=g01
Flow File=f01
Subcritical Flow
Calc Critical at every XS
Secant Critical Depth

--- 16051_ras.f01 (steady flow) ---

Flow Title=Flow 01
Program Version=5.01
Number of Profiles= 6
Profile Names=10yr,25yr,50yr,100yr,100plus,500yr
River Rch & RM=16051,18,8103.299
  811.96  992.94 1001.53 1108.88 1339.86  1449.8
River Rch & RM=16051,18,7871.315
  822.72 1006.06 1014.98 1123.84 1357.94 1468.74
River Rch & RM=16051,18,7639.332
 1146.58 1400.48 1420.49 1575.27 1903.41 2037.19
River Rch & RM=16051,18,7407.349
 1197.81 1462.83 1484.77  1646.9 1989.96 2126.87
River Rch & RM=16051,18,7175.365
 1207.15  1474.2  1496.5 1659.97 2005.74 2143.22
River Rch & RM=16051,18,6943.382
  1240.8 1515.15 1538.76 1707.06 2062.65  2202.1
River Rch & RM=16051,18,6711.399
  1250.8 1527.31 1551.31 1721.05 2079.55 2219.58
River Rch & RM=16051,18,6479.415
 1470.12 1794.13 1827.06 2028.51 2451.06 2602.75
River Rch & RM=16051,18,6247.432
 1488.13 1816.03 1849.73 2053.79  2481.6 2634.17
River Rch & RM=16051,18,6015.448
 1503.33 1834.52 1868.87 2075.14  2507.4  2660.7
River Rch & RM=16051,18,5783.465
 1524.03 1859.68 1894.93 2104.21 2542.52 2696.79
River Rch & RM=16051,18,5551.482
  1531.6 1868.89 1904.46 2114.85 2555.38 2710.01
River Rch & RM=16051,18,5319.498
 2242.18 2732.37 2801.55 3116.57 3765.77  3945.7
River Rch & RM=16051,18,5030.938
 2455.43  2991.3 3071.53 3418.36 4130.43 4315.34
River Rch & RM=16051,18,4825.666
 2469.99 3008.98 3089.98 3438.99 4155.35 4340.57
River Rch & RM=16051,18,4620.394
 2471.25 3010.51 3091.58 3440.78 4157.51 4342.76
River Rch & RM=16051,18,4415.122
 2672.32 3254.58 3346.44 3725.79 4501.89 4690.84
Boundary for River Rch & Prof#=16051,18,1
Up Type= 0
Dn Type= 2
Boundary for River Rch & Prof#=16051,18,2
Up Type= 0
Dn Type= 2
Boundary for River Rch & Prof#=16051,18,2
Up Type= 0
Dn Type= 2
Boundary for River Rch & Prof#=16051,18,2
Up Type= 0
Dn Type= 2
Boundary for River Rch & Prof#=16051,18,2
Up Type= 0
Dn Type= 2
Boundary for River Rch & Prof#=16051,18,2
Up Type= 0
Dn Type= 2

--- 16051_ras.g01 (geometry) ---

Geom Title=16051
Program Version=4.10

River Reach=16051,18
Reach XY= 30
767063.274737502859534.601180836767094.281371708859819.313733108
767136.306123193859909.562089699767385.780536381860135.459908365
767779.378616211860551.932152539 767918.40330481860740.873755391
768549.541849883861480.162543638768670.307197899861584.123293316
768776.338404144861711.887996443768841.948332811861822.920003674
769023.089613612862025.649108917769035.024413879862082.182989176
769130.998249797862130.802872355769202.849400341862187.074055083
769357.617135853862493.845215529769418.046037197862567.851264596
769522.212703854862752.313070148769535.233537227862882.521403477
769435.407148331863138.597792402769608.535411835863272.153055578
769731.825909348863347.579256768769942.621174186863750.963555523
770068.944644238 864091.70165961770260.553238451864961.942129523
770392.256288737865297.552119285770397.901685029865416.105441004
770203.135513693865811.283179909770086.414823025866008.669837385
770249.035208524866258.029971267770268.413526082866263.791338886

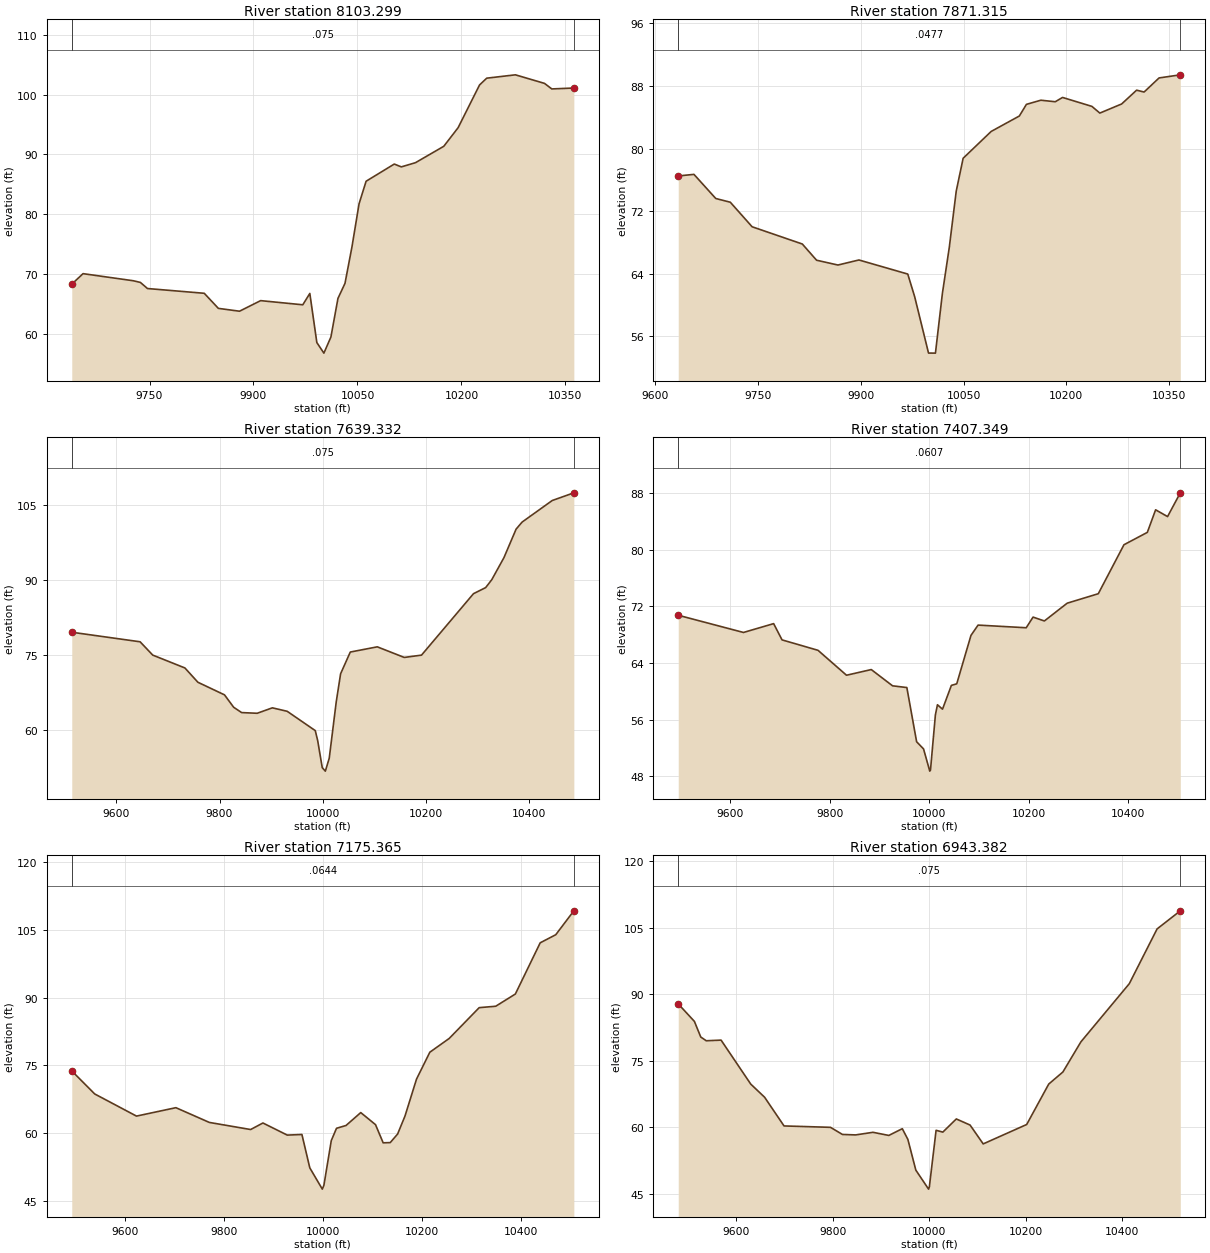
Type RM Length L Ch R = 1 ,8103.299,231.983400,231.983400,231.983400
XS GIS Cut Line= 6
 766709.26613991859609.794831741766800.113366592859585.786030485
766880.634887948859567.721438527767230.892625152859504.564686173
767330.986607105859478.884328646767415.324802433859452.023400082
#Sta/Elev= 30
9637.85668.31374 9654.1370.069449726.53368.88436 9736.8368.603719747.07867.58224
9828.96766.786879849.32564.264439879.86263.789789910.29165.558459971.12364.86298
9981.26266.75959  9991.458.5428210001.5556.78065 10011.759.4746410021.8565.93195
   1003268.4471810042.1574.60893 10052.381.7562610062.4585.5229910103.0788.39546
10113.2787.9232510133.6788.6259410174.5291.3672910195.1794.4742110226.14101.6286
10236.46102.757510277.83103.317510319.81101.8861 10330.3100.958810362.13101.1087
#Mann= 3 , 0 , 0
9637.856   0.075       09637.856   0.075       010362.13   0.075       0
#XS Ineff= 2 , 0
       0                               0
Bank Sta=9637.856,10362.13
Exp/Cntr=0.3,0.1

Type RM Length L Ch R = 1 ,7871.315,231.983300,231.983300,231.983300
XS GIS Cut Line= 6
766733.357536621859861.171733129766952.879924063859790.317258642
767151.681097603859757.060298469767224.196764291859739.528414575
767325.860695762 859703.35360683767433.386383778859656.272774705
#Sta/Elev= 30
9633.809 76.50049656.75376.702019688.55673.620769709.75973.145229741.56270.01134
9814.79967.808129835.59665.738359866.75365.124189897.39565.76878 9968.6263.97056
9978.71661.072799998.90653.88125   1000953.87288 10019.161.47488 10029.267.38146
10039.3174.5573810049.4178.7610110090.2582.18192 10131.484.1577910141.7185.64389
10162.7486.1726410183.7785.97747 10194.486.5269610237.1885.38653 10248.884.52982
10280.61  85.69310302.4487.4553810313.3687.2187410335.1989.0173910366.1889.41538
#Mann= 3 , 0 , 0
9633.809  0.0477       09633.809  0.0477       010366.18  0.0477       0
#XS Ineff= 2 , 0
       0                               0
Bank Sta=9633.809,10366.18
Exp/Cntr=0.3,0.1

Type RM Length L Ch R = 1 ,7639.332,231.983400,231.983400,231.983400
XS GIS Cut Line= 6
 766816.79243945860271.217420598 767076.90217047 860078.24326554
767240.922987776859910.605520723767302.741411364859856.637686888
767399.723682146859788.186096584767580.929514326859677.412623297
#Sta/Elev= 30
9514.00179.591349646.29777.680319670.74975.018869733.03472.448799758.18769.59172
9809.69467.072889827.37564.600389842.90363.528179872.97363.393829902.33964.48034
9931.05963.786859985.40559.926669990.02957.96105 9998.9452.5199910004.9251.83089
10012.46 54.419710026.04 65.706510034.4771.2899610053.21 75.629110105.4976.67039
10157.68 74.551510191.1175.0143810291.6487.2877310315.2788.5081510327.0890.08359
10350.71 94.503910374.19100.191910385.85101.604310444.12105.912410485.99107.4504
#Mann= 3 , 0 , 0
9514.001   0.075       09514.001   0.075       010485.99   0.075       0
#XS Ineff= 2 , 0
       0                               0
Bank Sta=9514.001,10485.99
Exp/Cntr=0.3,0.1

Type RM Length L Ch R = 1 ,7407.349,231.983400,231.983400,231.983400
XS GIS Cut Line= 6
766996.435116488860459.144601809767115.298600609860359.693459734
767209.583684619860274.044394673767527.866347746859958.253477231
767633.130346115859869.725280386767745.445940858 859785.14118746
#Sta/Elev= 30
9495.52370.73113 9626.6568.304949687.228  69.551 9704.14 67.25889776.46265.78786
 9833.68  62.2769883.451 63.07519926.23960.78261 9954.9460.538969974.57352.89933
9988.51551.88367   1000148.7569910002.4648.9196410012.3156.6905610016.4558.11221
10026.6157.4894810044.4360.8418510055.2161.06763 10083.8 67.8921 10098.169.34318
10194.8168.9699310208.5970.4718110231.2869.9256210277.13 72.432210339.6573.76673
10391.2480.6702210438.2182.4150510454.8485.5968210478.8784.6407210504.4787.99029
#Mann= 3 , 0 , 0
9495.523  0.0607       09495.523  0.0607       010504.47  0.0607       0
#XS Ineff= 2 , 0
       0                10098.67       0
Bank Sta=9495.523,10504.47
Exp/Cntr=0.3,0.1

Type RM Length L Ch R = 1 ,7175.365,231.983400,231.983400,231.983400
XS GIS Cut Line= 6
767146.374563345860625.549011704767303.306037134860488.557296793
 767523.68166406860287.176576392767727.365290176860102.947768419
767823.054351792860020.162255225767906.242156839859951.795679621
#Sta/Elev= 30
9492.15873.778539538.61268.668399623.07563.762449702.76665.629329770.497   62.36
9853.98560.786649878.868 62.23579928.10659.552819957.75459.685889973.69352.29537
    999947.5797510002.2548.4410710017.1658.3403210027.7461.0621310046.9761.68156
10076.7964.54202 10106.661.8716410122.1357.8409110136.4257.8911610151.3259.78729
10166.23 63.763810189.5571.9485510216.5277.9193510255.6780.9681510316.3687.79395
10349.85 88.110610389.5290.81433 10439.8102.1653 10471.3103.961510507.85109.2533
#Mann= 3 , 0 , 0
9492.158  0.0644       09492.158  0.0644       010507.85  0.0644       0
#XS Ineff= 2 , 0
       0                10082.62       0
Bank Sta=9492.158,10507.85
Exp/Cntr=0.3,0.1

Type RM Length L Ch R = 1 ,6943.382,231.983400,231.983400,231.983400
XS GIS Cut Line= 6
767299.600095396860802.820798783767418.659534658860700.548720908
   767549.645778860583.405160536767760.909539926  860379.9307883
767849.165950737860298.321319927768071.814176354860107.000914886
#Sta/Elev= 30
9480.10387.819529513.58883.866139526.771 80.33729538.14679.49736 9568.8479.64065
9630.22769.72061 9658.98 66.74329699.22760.265629795.392 59.95199820.135 58.3446
9847.58858.239749883.44658.828049916.22158.121799944.14859.64174 9955.6657.23002
9972.15150.296799998.52246.0002210000.16 46.508510014.1259.2799310028.0858.87184
10055.9961.8435410084.5160.4652710111.6856.2092710201.7560.5924110247.4169.71908
10276.7472.4463810314.0379.2504210414.2592.3812610471.79104.741610519.89108.8292
#Mann= 3 , 0 , 0
9480.103   0.075       09480.103   0.075       010519.89   0.075       0
#XS Ineff= 2 , 0
       0                10063.91       0
Bank Sta=9480.103,10519.89
Exp/Cntr=0.3,0.1

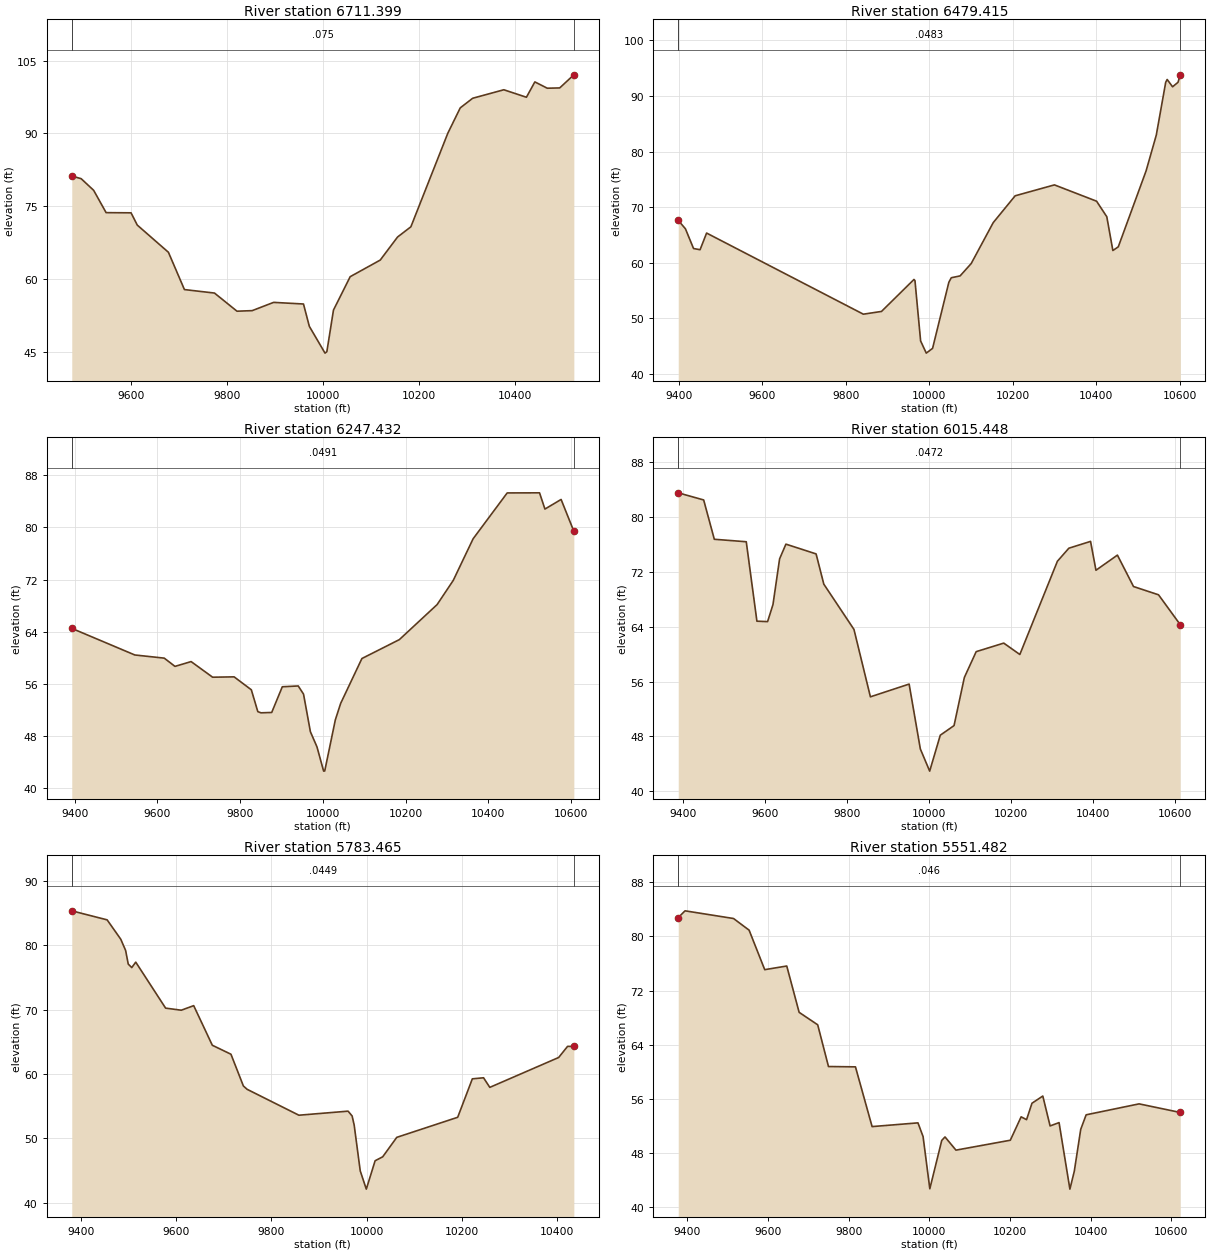
Type RM Length L Ch R = 1 ,6711.399,231.983400,231.983400,231.983400
XS GIS Cut Line= 6
767429.886083308860955.032521732767713.503506589860719.650134727
767783.708248692  860665.5601301767879.231513508 860599.22728079
767941.752613588860552.343333475768247.725285005860302.096967917
#Sta/Elev= 30
9476.54381.245169496.184 80.69169522.17478.300259548.16573.706919600.14673.67042
9613.14271.146079678.11865.546569711.46957.874859774.10257.159639821.07753.42432
9852.73253.540059897.49755.241299959.71754.905059971.918 50.309210004.62 44.7964
10008.46 45.096510022.2453.6541610057.0860.5271910119.74 63.944210155.8968.69243
10183.64 70.7918 10260.790.0549310286.6295.2714410312.54 97.247810377.4498.99625
 10424.697.4561910442.16100.612310468.09 99.314310494.0199.3754710523.46102.0698
#Mann= 3 , 0 , 0
9476.543   0.075       09476.543   0.075       010523.46   0.075       0
#XS Ineff= 2 , 0
       09912.152        10066.18       0
Bank Sta=9476.543,10523.46
Exp/Cntr=0.3,0.1

Type RM Length L Ch R = 1 ,6479.415,231.983400,231.983400,231.983400
XS GIS Cut Line= 6
767521.741264041861198.441723095 767864.44747894 860913.13182749
767935.712284418860850.975759845768039.569416881860756.637935803
768120.894039896  860686.7306265768439.240817226860422.670143528
#Sta/Elev= 30
9399.17867.59817 9416.43 66.07429435.81662.521589451.446 62.30849467.07565.30798
9842.18450.694499885.64451.187859963.37656.949219965.76856.741289979.30145.86773
9992.83443.6781710007.9144.5371410046.8356.4340110052.6157.2558110073.8157.59194
10100.3259.8117410153.0767.1880710205.5972.0225310299.5773.9858110400.4371.04816
10424.8868.24871 10439.462.16263 10452.462.8308110518.8676.4969110543.3482.95699
10565.8592.4630510569.3392.9766610582.3291.6614410595.3192.4649410600.8293.81412
#Mann= 3 , 0 , 0
9399.178  0.0483       09399.178  0.0483       010600.82  0.0483       0
#XS Ineff= 2 , 0
       09943.858        10083.86       0
Bank Sta=9399.178,10600.82
Exp/Cntr=0.3,0.1

Type RM Length L Ch R = 1 ,6247.432,231.983400,231.983400,231.983400
XS GIS Cut Line= 6
767662.969433586861372.451730443768031.391251016861066.475356838
768130.567089216860986.847793317768132.139442756860985.611789942
 768241.07583558860897.827834397768598.623270034860598.668937441
#Sta/Elev= 30
9392.90264.497769545.43360.409779616.52559.925049642.52358.65711 9681.5259.39498
9733.51656.994459785.51257.048829827.16755.058429842.81951.705819850.50751.52294
9876.44251.57797 9902.0955.525879940.56355.650319953.38854.396399970.00648.61645
9985.97946.2776410001.9842.5638410004.6742.5885710030.3650.45657 10043.252.97045
10094.5759.8650910185.1462.7700510276.4168.1504610315.5271.8728810363.4878.26081
10445.9185.3085110524.1485.3242810537.1882.82863 10576.384.30459 10607.179.41963
#Mann= 3 , 0 , 0
9392.902  0.0491       09392.902  0.0491       0 10607.1  0.0491       0
#XS Ineff= 2 , 0
       09945.792                       0
Bank Sta=9392.902,10607.1
Exp/Cntr=0.3,0.1

Type RM Length L Ch R = 1 ,6015.448,231.983400,231.983400,231.983400
XS GIS Cut Line= 6
767817.219289252861563.171191051 767980.61772243 861427.75928409
 768128.43857374861301.607185628768216.678478164861223.315682782
768419.106728097861037.071454303768742.213381303860760.728343296
#Sta/Elev= 30
9387.61683.530849449.672 82.48829475.64776.753659553.57376.392429579.548 64.8026
9605.59364.740249618.73967.229889634.89273.898649650.29676.043379723.91274.61955
9742.72470.210769816.30563.598819856.41153.766769950.85755.626769978.20646.16793
   10001 42.926210026.8448.1675910060.4449.5683910085.5956.5933110114.4760.35927
10181.6961.6036610220.9359.9448710312.5773.5474110340.5475.4512110393.4576.44523
10406.6172.2337410458.9774.4418810498.2369.8593110559.2768.6525310612.3964.28469
#Mann= 3 , 0 , 0
9387.616  0.0472       09387.616  0.0472       010612.39  0.0472       0
#XS Ineff= 2 , 0
       09949.713                       0
Bank Sta=9387.616,10612.39
Exp/Cntr=0.3,0.1

Type RM Length L Ch R = 1 ,5783.465,231.983400,231.983400,231.983400
XS GIS Cut Line= 6
767957.604519643861730.427750876 768096.20463911861616.391625415
 768344.03773719861408.527010438768436.282968252861335.553505376
768535.590672941861256.104484971768769.270534506861056.450895695
#Sta/Elev= 30
9380.43385.354649454.759 83.95039483.411 80.93989493.60879.19429 9499.1577.06717
9506.557 76.53379514.88977.377029577.64370.228799610.55169.904039636.65470.61383
9675.809 64.45569714.96463.061069741.06858.127129748.81757.612569857.74653.57937
9961.13454.210059969.61653.457489973.88852.056499986.64344.929789999.39142.08898
10017.89 46.4976 10033.947.1161810063.3950.1363910191.4653.2575210222.2459.23612
10245.7859.3998310258.9357.9086310403.6162.5524810422.3764.2842410435.5364.27181
#Mann= 3 , 0 , 0
9380.433  0.0449       09380.433  0.0449       010435.53  0.0449       0
#XS Ineff= 2 , 0
       09947.368        10116.21       0
Bank Sta=9380.433,10435.53
Exp/Cntr=0.3,0.1

Type RM Length L Ch R = 1 ,5551.482,231.983500,231.983500,231.983500
XS GIS Cut Line= 6
768118.685229672 861925.63978778768438.344879077861658.934113392
768524.173567083861578.026564888768638.137705818861454.826403143
768713.596201166861381.001320486769042.811419021861094.230564739
#Sta/Elev= 30
9377.83982.788999394.70683.788239514.85182.654649553.51380.934059592.17575.10458
9646.79675.641539677.48168.80522 9723.51 66.96499750.22160.806849817.07660.75807
9858.30551.940549971.997  52.491 9984.6550.4714310001.3642.7604210030.9549.90307
10039.0250.4105710066.1648.4660810200.8449.9275410227.6953.3817710241.1252.96313
10254.5455.3877310281.3956.4528710299.4552.0370710321.6752.5300110348.5242.71093
 10359.445.3375410375.3751.5331810388.7953.6796610520.0555.2946110622.17 54.0242
#Mann= 3 , 0 , 0
9377.839   0.046       09377.839   0.046       010622.17   0.046       0
#XS Ineff= 2 , 0
       09956.408        10137.57       0
Bank Sta=9377.839,10622.17
Exp/Cntr=0.3,0.1

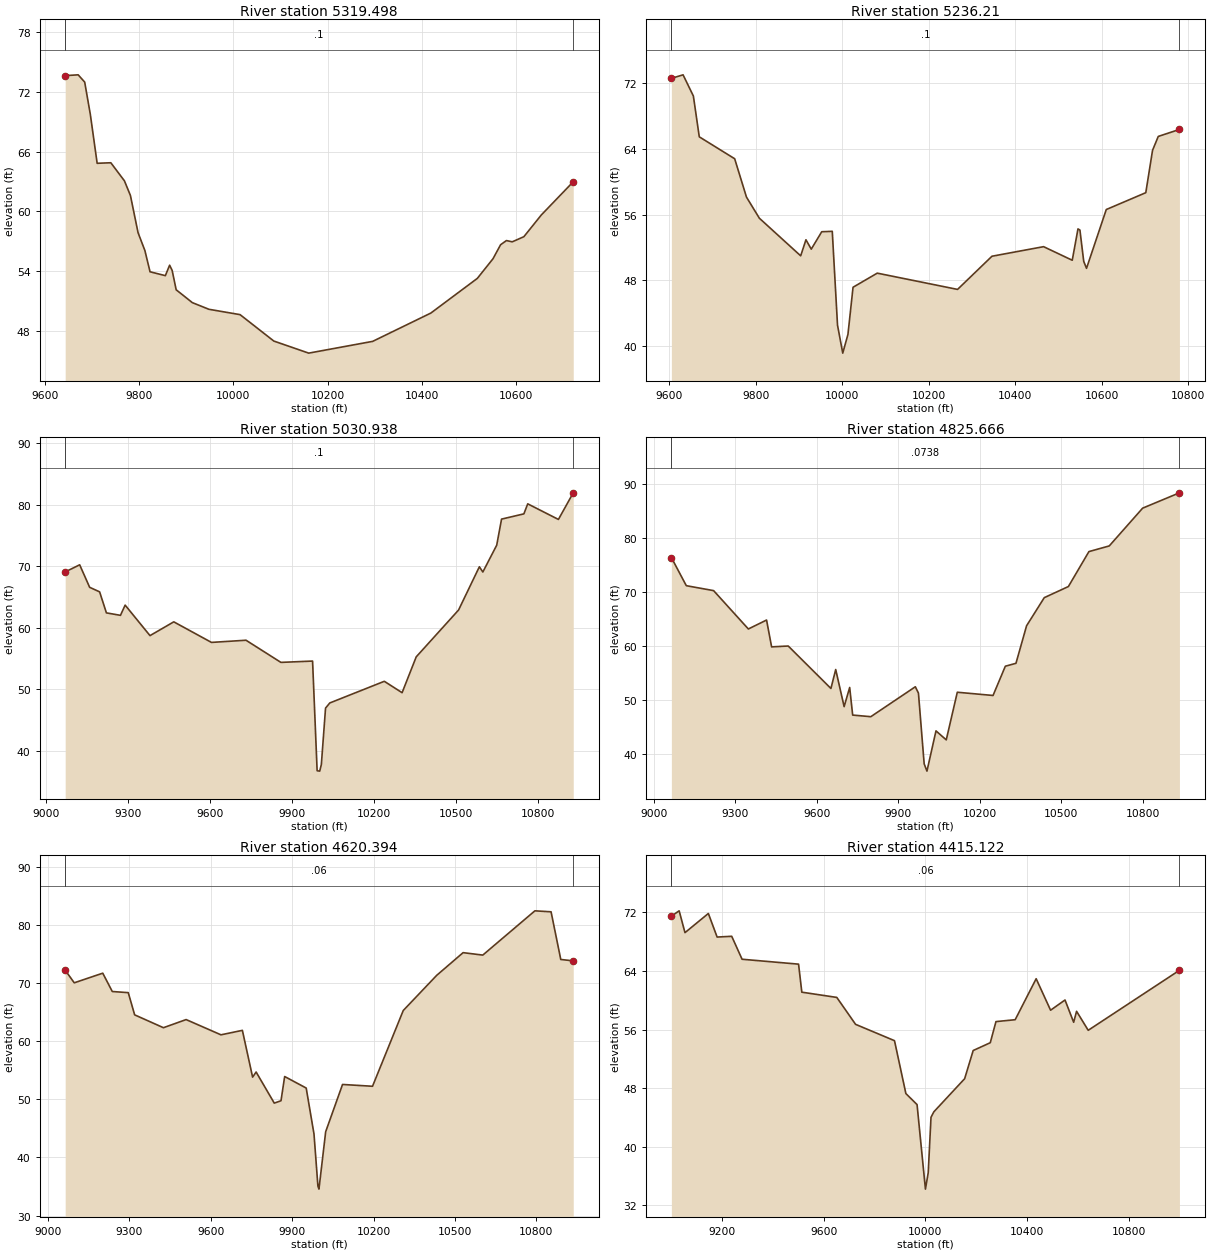
Type RM Length L Ch R = 1 ,5319.498,83.287800,83.287800,83.287800
XS GIS Cut Line= 4
768498.127498031861934.857829481768684.636408836861740.200471088
  768795.9985255861625.216822192769174.448645562861100.094646052
#Sta/Elev= 30
9643.61873.64777 9671.1273.729789684.96972.996459696.91569.74778 9711.3764.82892
9740.36764.881459769.18763.063349781.91461.587349798.09657.84183 9812.5556.05062
9823.46253.913779855.91353.52225 9865.01 54.57459870.36854.04618 9878.8652.10079
9913.20550.806219948.28750.1378410014.3549.5986210085.87 46.941810159.8345.72743
10295.4246.9109610418.6849.7579410517.2953.2493410550.4755.22506 10566.656.63584
10578.9257.0526510591.2556.92704 10615.957.4430810652.8859.6288310720.5662.97043
#Mann= 3 , 0 , 0
9643.618     0.1       09643.618     0.1       010720.56     0.1       0
#XS Ineff= 2 , 0
       09948.187        10159.92       0
Bank Sta=9643.618,10720.56
Exp/Cntr=0.3,0.1

Type RM Length L Ch R = 1 , 5236.21,205.272200,205.272200,205.272200
XS GIS Cut Line= 6
768506.587703854862012.295709029768685.686742306861819.290704578
768783.035233974861751.730550036768801.896328509861738.927887186
768839.601228982861715.357550994769316.049509376861168.111681253
#Sta/Elev= 30
 9605.1472.603439632.20973.03795 9656.0270.453989669.662 65.47559751.515 62.8007
  9778.858.121299808.62655.544539904.12250.957359916.29552.915569928.585 51.7742
9952.81153.897079977.156 53.94679989.28542.5045310001.3939.0897210013.3941.37119
10025.1947.1257610081.1948.8459110266.8246.8617110346.3750.90824 10465.752.07612
10531.9950.4190910545.2554.2437110549.7554.1041710558.5150.2855610564.9849.43072
10610.6756.6061810702.0458.6611510717.6263.8262510730.8865.5231210779.7966.37637
#Mann= 3 , 0 , 0
 9605.14     0.1       0 9605.14     0.1       010779.79     0.1       0
#XS Ineff= 2 , 0
       09957.391        10187.81       0
Bank Sta=9605.14,10779.79
Exp/Cntr=0.3,0.1

Type RM Length L Ch R = 1 ,5030.938,205.272100,205.272100,205.272100
XS GIS Cut Line= 6
768171.423609344862471.241801566768405.874858565862305.788475357
768679.456669773862098.980015472 768857.92962717861956.927116665
769301.072088397861585.194835405769638.514240617861326.562984972
#Sta/Elev= 30
9069.17569.07134 9122.2670.229779158.80566.574079195.35165.836639220.18862.42134
9271.68862.022749288.84863.682469379.94558.728269467.08960.965379605.18957.62521
9731.74857.980699859.55754.382059975.64654.59584 9992.3436.78549 10001.836.72243
10007.7937.8018810023.1946.9552110038.5947.78804 10238.551.3094810303.6849.45971
10355.4455.2790810510.6362.8878410586.8569.9117710599.5669.0579610650.3773.41638
 10668.177.6491110749.91 78.500410764.0280.1285610876.4677.5968710930.8281.91834
#Mann= 3 , 0 , 0
9069.175     0.1       09069.175     0.1       010930.82     0.1       0
#XS Ineff= 2 , 0
       0                10184.94       0
Bank Sta=9069.175,10930.82
Exp/Cntr=0.3,0.1

Type RM Length L Ch R = 1 ,4825.666,205.272200,205.272200,205.272200
XS GIS Cut Line= 6
768269.138653008862610.902644743768658.371130582862345.489623195
768972.191018946862096.406279402769073.731769288862049.932476651
  769367.3473291861790.928490295769765.131807847861497.074463866
#Sta/Elev= 30
 9064.5676.432559119.57771.220019220.06770.308269348.04863.211879415.10964.86597
9433.70359.902259494.88660.061379652.09952.206219669.72755.710259700.71648.84825
9721.16952.389929732.15447.286789798.93646.985859962.93752.521979974.38351.34546
9995.42738.2710310005.7136.9170510038.9544.3607310076.7842.6994110117.4551.50965
10249.0850.9119110294.3656.3254910333.4556.8599910372.5463.8052310437.6969.00452
10526.5571.0635910602.1377.5256610677.0578.5765810799.9985.5632610935.3888.39802
#Mann= 3 , 0 , 0
 9064.56  0.0738       0 9064.56  0.0738       010935.38  0.0738       0
#XS Ineff= 2 , 0
       09967.555        10157.33       0
Bank Sta=9064.56,10935.38
Exp/Cntr=0.3,0.1

Type RM Length L Ch R = 1 ,4620.394,205.272100,205.272100,205.272100
XS GIS Cut Line= 6
768436.648854857862722.284089548768948.615076256862395.948470083
769073.099241584862298.112022124769260.038202285862122.938017919
769398.871251475 862010.20359967769953.543478778861632.641506906
#Sta/Elev= 30
9064.07372.196819097.40170.024959202.49371.68105 9237.5868.526769296.42668.33615
9319.99164.517329426.02962.30874 9509.6263.705169638.05261.084379716.89561.85352
 9754.5453.81444 9767.4854.692129834.36849.346869859.20549.755039872.66953.91795
9952.00251.937649980.777 44.03139995.16535.10043    9999 34.563310023.7944.43065
10085.9452.5531710196.3952.2426510309.6165.2619810432.7471.3042110530.12  75.209
10602.6874.7887210794.63 82.397610854.2382.2276410889.9974.0327610935.9373.80153
#Mann= 3 , 0 , 0
9064.073    0.06       09064.073    0.06       010935.93    0.06       0
#XS Ineff= 2 , 0
       09912.812                       0
Bank Sta=9064.073,10935.93
Exp/Cntr=0.3,0.1

Type RM Length L Ch R = 1 ,4415.122,0.000000,0.000000,0.000000
XS GIS Cut Line= 6
768418.352694957862842.686398962769110.093367557862451.392033664
769222.169283365862394.135831189 769442.60886698 862291.73719477
769596.724639335862213.390218168770178.228488685861891.672579581
#Sta/Elev= 30
8999.42671.469089030.08172.200499053.08969.221899145.12271.838989179.63468.62096
9237.15468.723499277.94465.591219500.45664.921529513.251 61.09669651.02760.38107
9725.04556.706029878.29154.477749923.14547.258249967.16245.7530810000.1634.21516
10011.1336.4609910022.1144.0212610033.0844.7574710154.67 49.290510188.2253.13384
10255.5354.1977510277.9657.0789710353.6657.3393410436.2962.93364 10493.158.63493
10549.9160.03015   1058456.9875410595.4658.4859410641.3455.8943611000.5864.08092
#Mann= 3 , 0 , 0
8999.426    0.06       08999.426    0.06       011000.58    0.06       0
#XS Ineff= 2 , 0
       0                               0
Bank Sta=8999.426,11000.58
Exp/Cntr=0.3,0.1